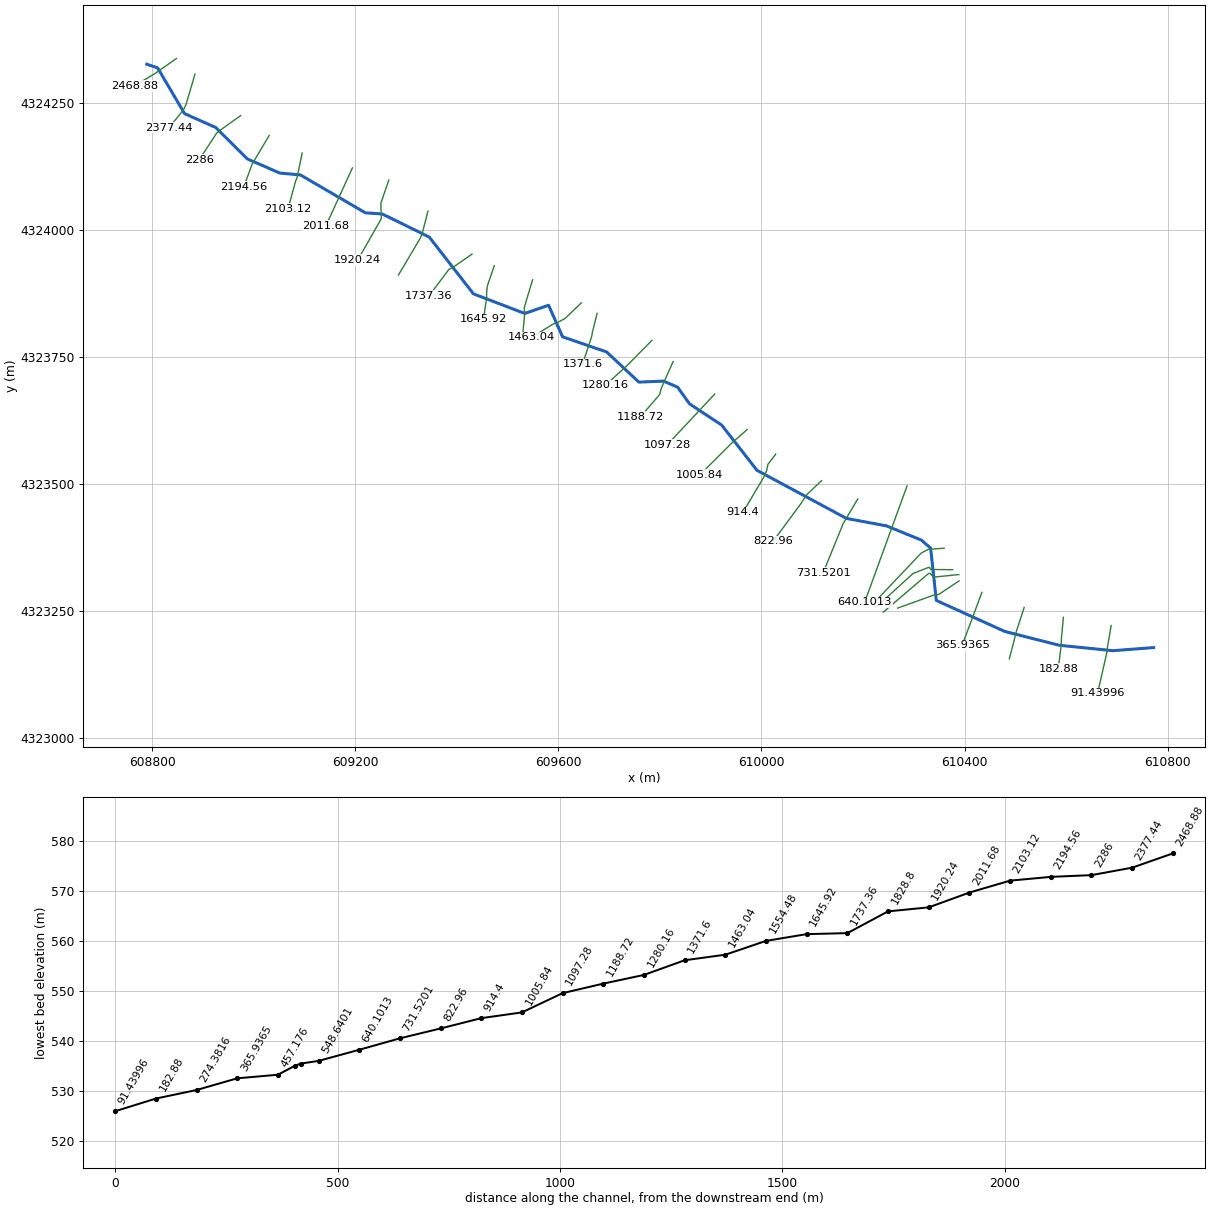
--- LaurelRunShv.prj (project) ---

Proj Title=LaurelRunShv
Current Plan=p01
Default Exp/Contr=0.3,0.1
SI Units
Geom File=g01
Flow File=f01
Plan File=p01
Y Axis Title=Elevation
X Axis Title(PF)=Main Channel Distance
X Axis Title(XS)=Station
BEGIN DESCRIPTION:
September 2018
Tucker County ABFE Study
US Army Corps of Engineers, Pittsburgh District
NAD 1983 UTM 17N (meters)
END DESCRIPTION:
DSS Export Rating Curves= 0
DSS Export Rating Curve Sorted= 0
DSS Export Volume Flow Curves= 0
DXF OffsetX= 0
DXF OffsetY= 0
DXF ScaleX= 1
DXF ScaleY= 10

--- LaurelRunShv.p01 (plan) ---

Plan Title=LaurelRunShv_plan
Program Version=5.05
Short Identifier=Plan1_subcritical
Geom File=g01
Flow File=f01
Subcritical Flow
K Sum by GR= 0
Std Step Tol= 0.003
Critical Tol= 0.003
Num of Std Step Trials= 20
Max Error Tol= 0.1
Flow Tol Ratio= 0.001
Split Flow NTrial= 30
Split Flow Tol= 0.006
Split Flow Ratio= 0.02
Log Output Level= 0
Friction Slope Method= 1
Unsteady Friction Slope Method= 2
Unsteady Bridges Friction Slope Method= 1
Parabolic Critical Depth
Global Vel Dist= 0 , 0 , 0
Global Log Level= 0
CheckData=True
Encroach Param=-1 ,0,0, 0
Computation Interval=1MIN
Output Interval=1HOUR
Instantaneous Interval=1HOUR
Mapping Interval=1HOUR
Computation Time Step Use Courant=        0
Computation Time Step Use Time Series=    0
Computation Time Step Count To Double=0
Computation Time Step Max Doubling=0
Computation Time Step Max Halving=0
Computation Time Step Residence Courant=0
Run HTab= 0
Run UNet= 0
Run Sediment= 0
Run PostProcess= 0
Run WQNet= 0
Run RASMapper=-1
UNET Theta= 1
UNET Theta Warmup= 1
UNET ZTol= 0.006
UNET ZSATol= 0.006
UNET MxIter= 20
UNET Max Iter WO Improvement= 0
UNET MaxInSteps= 0
UNET DtIC= 0
UNET DtMin= 0
UNET MaxCRTS= 20
UNET WFStab= 2
UNET SFStab= 1
UNET WFX= 1
UNET SFX= 1
UNET 1D Methodology=Finite Difference
UNET DSS MLevel= 4
UNET Pardiso=0
UNET DZMax Abort= 30
UNET Use Existing IB Tables=-1
UNET Froude Reduction=False
UNET Froude Limit= 0.8
UNET Froude Power= 4
UNET D1 Cores= 0
UNET D2 Coriolis=0
UNET D2 Cores= 0
UNET D2 Theta= 1
UNET D2 Theta Warmup= 1
UNET D2 Z Tol= 0.003
UNET D2 Volume Tol= 0.003
UNET D2 Max Iterations= 20
UNET D2 Equation= 0
UNET D2 RampUpFraction=0.1
UNET D2 TimeSlices= 1
UNET D2 BCVolumeCheck=0
UNET D1D2 MaxIter= 0
UNET D1D2 ZTol=0.003
UNET D1D2 QTol=0.1
UNET D1D2 MinQTol=0.03
Write IC File= 0
Write IC File at Fixed DateTime=0
Write IC File at Sim End=0
Echo Input=False
Echo Parameters=False
Echo Output=False
Write Detailed= 0
HDF Write Warmup=0
HDF Write Time Slices=0
HDF Flush=0
HDF Face Node Velocities=0
HDF Compression= 1
HDF Chunk Size= 1
HDF Spatial Parts= 1
HDF Use Max Rows=0
HDF Fixed Rows= 1
Calibration Method= 0
Calibration Iterations= 20
Calibration Max Change=0.05
Calibration Tolerance=0.2
Calibration Maximum=1.5
Calibration Minimum=0.5
Calibration Optimization Method= 1
WQ AD Non Conservative
WQ ULTIMATE=-1
WQ Max Comp Step=1HOUR
WQ Output Interval=15MIN
WQ Output Selected Increments= 0
WQ Output face flow=0
WQ Output face velocity=0
WQ Output face area=0
WQ Output face dispersion=0
WQ Output cell volume=0
WQ Output cell surface area=0
WQ Output cell continuity=0
WQ Output cumulative cell continuity=0
WQ Output face conc=0
WQ Output face dconc_dx=0
WQ Output face courant=0
WQ Output face peclet=0
WQ Output face adv mass=0
WQ Output face disp mass=0
WQ Output cell mass=0
WQ Output cell source sink temp=0
WQ Output nsm pathways=0
WQ Output nsm derived pathways=0
WQ Output MaxMinRange=-1
WQ Daily Max Min Mean=-1
WQ Daily Range=0
WQ Daily Time=0
WQ Create Restart=0
WQ Fixed Restart=0
WQ System Summary=0
WQ Write To DSS=0
WQ Use Fixed Temperature=0
Sorting and Armoring Iterations= 10
XS Update Threshold= 0.02
Bed Roughness Predictor= 0
Hydraulics Update Threshold= 0.02
Energy Slope Method= 1
Volume Change Method= 1
Sediment Retention Method= 0
XS Weighting Method= 0
Number of US Weighted Cross Sections= 1
Number of DS Weighted Cross Sections= 1
Upstream XS Weight=0
Main XS Weight=1
Downstream XS Weight=0
Number of DS XS's Weighted with US Boundary= 1
Upstream Boundary Weight= 1
Weight of XSs Associated with US Boundary= 0
Number of US XS's Weighted with DS Boundary= 1
Downstream Boundary Weight= 0.5
Weight of XSs Associated with DS Boundary= 0.5
Percentile Method= 0
Sediment Output Level= 4
Mass or Volume Output= 0
Output Increment Type= 1
Profile and TS Output Increment= 1
XS Output Flag= 0
XS Output Increment= 10
Write Gradation File= 0
Read Gradation Hotstart= 0
Write HDF5 File= 1
Write Binary Output= 1
Write DSS Sediment File= 0
SV Curve= 0
Specific Gage Flag= 0

--- LaurelRunShv.f01 (steady flow) ---

Flow Title=LaurelRunShv_flow
Program Version=5.05
Number of Profiles= 1
Profile Names=PF 1
River Rch & RM=Laurel Run (Shv),1               ,2468.88
   14.64
River Rch & RM=Laurel Run (Shv),1               ,1463.04
 18.9721
River Rch & RM=Laurel Run (Shv),1               ,1188.72
 19.4252
River Rch & RM=Laurel Run (Shv),1               ,274.3816
  21.464
River Rch & RM=Laurel Run (Shv),1               ,91.43996
 21.6056
Boundary for River Rch & Prof#=Laurel Run (Shv),1               , 1
Up Type= 2
Dn Type= 1
Dn Known WS=524.8
DSS Import GetInterval= 0
DSS Import GetPeak= 0
DSS Import FillOption= 0

--- LaurelRunShv.g01 (geometry) ---

Geom Title=LaurelRunShv_geometry
Program Version=5.05

River Reach=Laurel Run (Shv),1
Reach XY= 30
     608789.7896    4324325.4546608811.2399183134324317.91917207
608864.1548838024324228.13896526     608925.6516    4324200.8229
     608987.6849     4324139.063     609051.6145    4324111.2765
609092.3233115034324107.53435798     609220.0673    4324033.0767
     609253.6033    4324030.6955      609345.943    4323985.3194
609433.0424488264323873.59311174     609533.9034    4323835.0622
     609580.8935    4323851.1753     609608.5148    4323789.0729
     609695.2607     4323759.284     609758.6939    4323699.9657
     609807.1127    4323701.9501      609834.894    4323690.0438
609858.557334976 4323657.1429723     609921.8098    4323615.4311
     609991.2631    4323526.5309     610167.3981     4323431.823
610246.1057138514323417.18521385     610314.9815    4323389.2119
     610333.1963    4323373.4857     610344.4164    4323270.4469
     610479.0482    4323209.5264610586.4967328194323182.23300894
 610692.045484484323171.61567889     610772.3146    4323177.6771

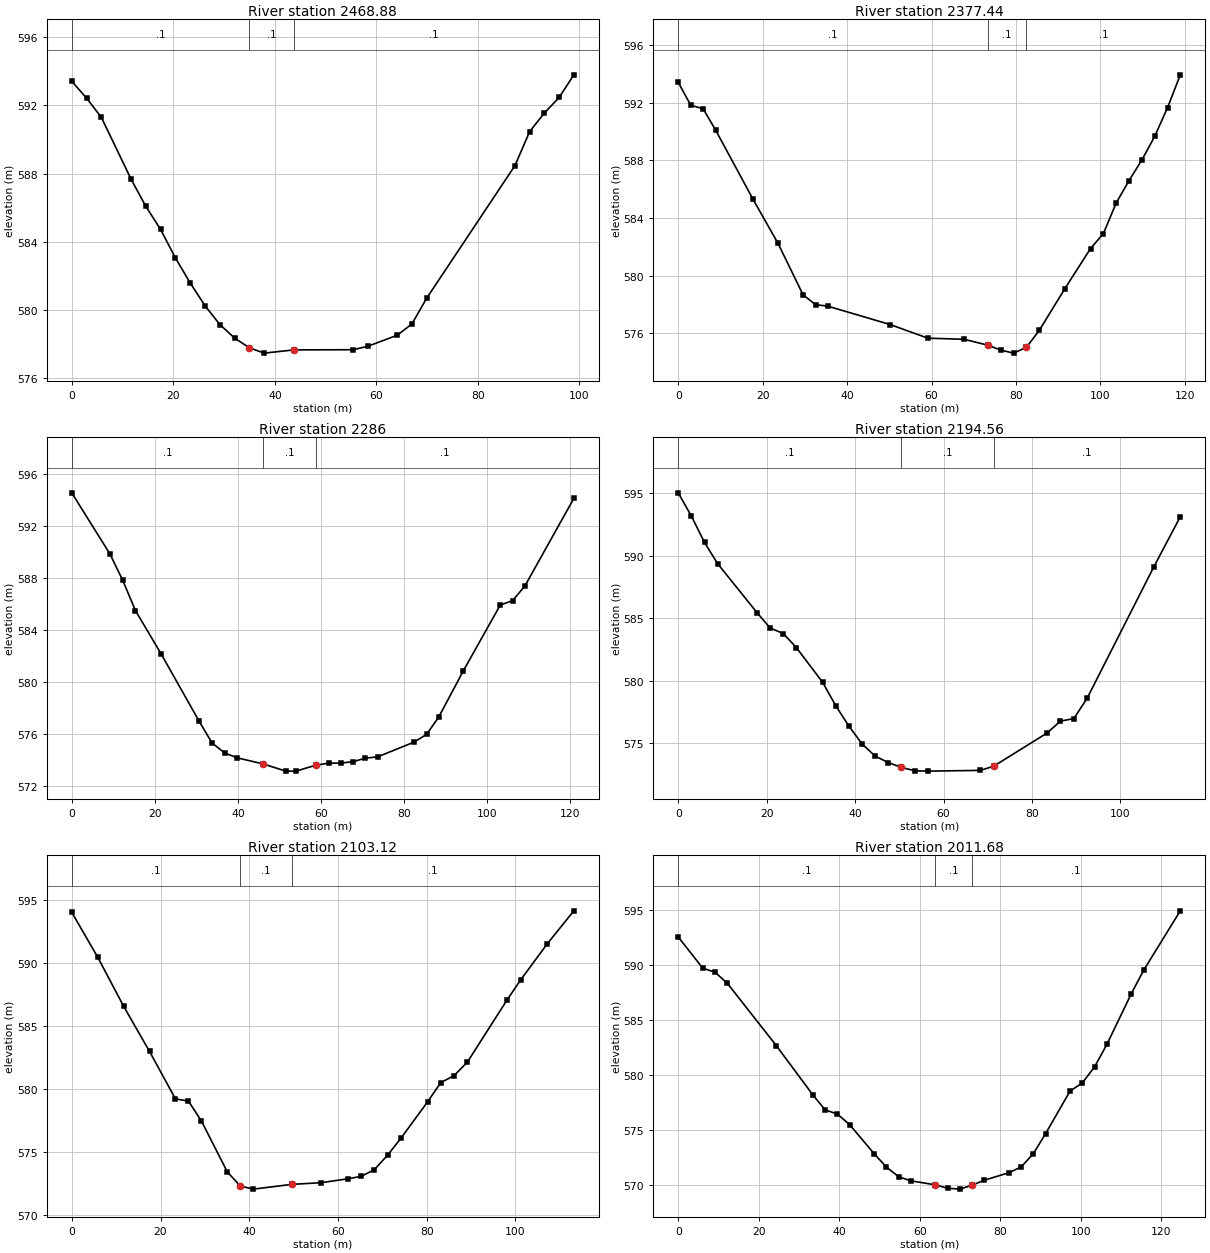
Type RM Length L Ch R = 1 ,2468.88 ,83.72,91.44,93.25
XS GIS Cut Line= 3
     608848.0221     4324336.658      608805.018    4324306.5509
     608765.2914     4324282.588
#Sta/Elev= 24
       0  593.42    2.92  592.43    5.83   591.3   11.67  587.68   14.58  586.08
    17.5  584.72   20.41  583.05   23.33  581.58   26.25  580.24   29.16  579.14
   32.08  578.34      35  577.77   37.91  577.46   43.75  577.65    55.4  577.66
   58.29  577.86   64.09  578.51   66.99  579.17   69.89  580.68   87.29  588.47
   90.19  590.47   93.09  591.56   95.99  592.47   98.89   593.8
#Mann= 3 , 0 , 0
       0      .1       0      35      .1       0   43.75      .1       0
Bank Sta=35,43.75
XS Rating Curve= 0 ,0
Exp/Cntr=0.3,0.1

Type RM Length L Ch R = 1 ,2377.44 ,92.59,91.44,83.59
XS GIS Cut Line= 4
     608884.5447    4324305.6495     608866.9561    4324246.1047
     608862.1299    4324235.9082     608833.5417    4324200.4274
#Sta/Elev= 26
       0  593.43    2.96  591.84    5.91  591.59    8.87   590.1   17.74  585.29
   23.65  582.23   29.57  578.66   32.52  577.98   35.48  577.87   50.26  576.59
   59.13  575.65   67.73  575.57   73.37  575.16   76.41  574.82   79.44  574.61
   82.48  575.01   85.52  576.19    91.6   579.1   97.67  581.88  100.71  582.92
  103.75  585.05  106.78   586.6  109.82  588.03  112.86  589.67   115.9  591.67
  118.93  593.95
#Mann= 3 , 0 , 0
       0      .1       0   73.37      .1       0   82.48      .1       0
Bank Sta=73.37,82.48
XS Rating Curve= 0 ,0
Exp/Cntr=0.3,0.1

Type RM Length L Ch R = 1 ,2286    ,89.57,91.44,94.86
XS GIS Cut Line= 4
     608974.5032    4324224.2899     608934.5625    4324195.8046
     608927.0743    4324189.4865     608893.1437    4324137.6387
#Sta/Elev= 26
       0  594.57     9.2  589.85   12.26  587.83   15.33  585.49   21.46  582.18
   30.66  576.96   33.73   575.3   36.79  574.52   39.86  574.14   45.99  573.68
   51.51  573.12   53.96  573.12   58.86  573.59   61.81  573.73   64.76  573.74
   67.71  573.85   70.66  574.12   73.61  574.22   82.46  575.37   85.41  575.96
   88.36  577.32   94.26  580.87  103.11  585.92  106.07  586.26  109.02  587.38
  120.82  594.14
#Mann= 3 , 0 , 0
       0      .1       0   45.99      .1       0   58.86      .1       0
Bank Sta=45.99,58.86
XS Rating Curve= 0 ,0
Exp/Cntr=0.3,0.1

Type RM Length L Ch R = 1 ,2194.56 ,90.57,91.44,92.25
XS GIS Cut Line= 3
     609030.8128    4324185.2455      608997.342    4324129.1231
     608980.5887    4324083.9282
#Sta/Elev= 25
       0  595.04    2.97  593.18    5.94  591.07    8.91  589.37   17.82  585.45
   20.79  584.22   23.76  583.78   26.73  582.65   32.67  579.87   35.64  577.99
   38.61  576.37   41.58  574.94   44.55  573.97   47.52  573.45   50.49  573.07
   53.46   572.8   56.43  572.77   68.36  572.83   71.37  573.17   83.42  575.82
   86.43  576.77   89.45  576.97   92.46  578.59  107.52  589.09  113.55  593.13
#Mann= 3 , 0 , 0
       0      .1       0   50.49      .1       0   71.37      .1       0
Bank Sta=50.49,71.37
XS Rating Curve= 0 ,0
Exp/Cntr=0.3,0.1

Type RM Length L Ch R = 1 ,2103.12 ,92.23,91.44,91.04
XS GIS Cut Line= 4
     609095.6826    4324150.6033     609085.6001    4324101.9778
     609082.9732    4324096.0163     609067.9013    4324041.0656
#Sta/Elev= 25
       0  594.02    5.84  590.46   11.68  586.56   17.53  582.96   23.37  579.19
   26.29  579.02   29.21  577.44   35.05  573.39   37.98  572.27    40.9  572.02
   49.66   572.4   56.17  572.53   62.17  572.84   65.17  573.03   68.17  573.56
   71.17  574.72   74.17  576.06   80.17  578.95   83.17  580.49   86.16  581.04
   89.16  582.12   98.16  587.09  101.16  588.65  107.16  591.52  113.15  594.14
#Mann= 3 , 0 , 0
       0      .1       0   37.98      .1       0   49.66      .1       0
Bank Sta=37.98,49.66
XS Rating Curve= 0 ,0
Exp/Cntr=0.3,0.1

Type RM Length L Ch R = 1 ,2011.68 ,89.98,91.44,93.62
XS GIS Cut Line= 2
     609194.6477    4324121.3509     609142.6983    4324008.0074
#Sta/Elev= 29
       0  592.52    6.08  589.69    9.12  589.32   12.16  588.33   24.33  582.67
   33.45  578.18   36.49  576.83   39.53  576.45   42.57  575.49   48.66  572.85
    51.7  571.64   54.74  570.76   57.78  570.39   63.86  570.03    66.9  569.72
   69.94  569.64   72.98     570   76.03  570.45   82.11  571.13   85.15  571.65
   88.19  572.86   91.23  574.68   97.31  578.54  100.35  579.28  103.39  580.73
  106.44  582.77  112.52  587.38  115.56  589.49  124.68  594.89
#Mann= 3 , 0 , 0
       0      .1       0   63.86      .1       0   72.98      .1       0
Bank Sta=63.86,72.98
XS Rating Curve= 0 ,0
Exp/Cntr=0.3,0.1

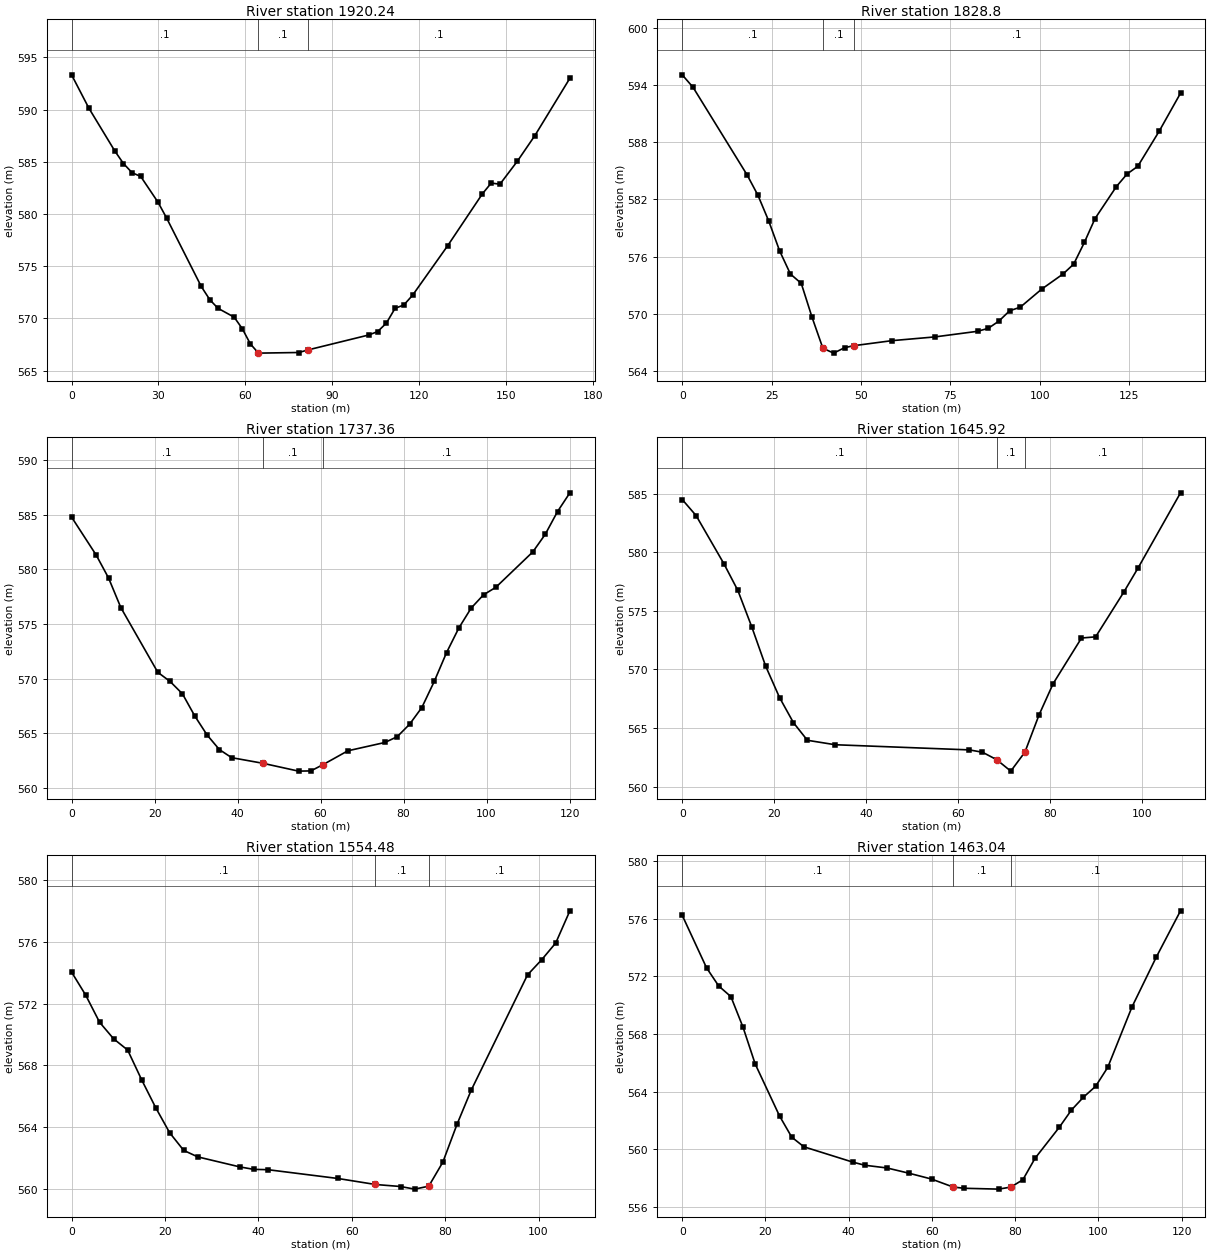
Type RM Length L Ch R = 1 ,1920.24 ,92.69,91.44,85.79
XS GIS Cut Line= 4
     609266.3392     4324097.422     609250.6902    4324052.2879
     609251.5325    4324021.5463     609205.2204    4323940.2591
#Sta/Elev= 30
       0  593.32    5.97  590.13   14.93  586.03   17.91  584.83    20.9  583.95
   23.88  583.59   29.86  581.12   32.84   579.6   44.78  573.06   47.77  571.78
   50.57  570.97   56.16  570.12   58.95  569.02   61.75  567.56   64.54  566.68
   78.52  566.74   81.54  566.98  102.67  568.42  105.68  568.74   108.7  569.55
  111.72  570.97  114.74  571.29  117.76  572.22  129.83  576.94   141.9  581.94
  144.92  582.96  147.93  582.85  153.97  585.06  160.01  587.51  172.08  592.99
#Mann= 3 , 0 , 0
       0      .1       0   64.54      .1       0   81.54      .1       0
Bank Sta=64.54,81.54
XS Rating Curve= 0 ,0
Exp/Cntr=0.3,0.1

Type RM Length L Ch R = 1 ,1828.8  ,97.33,91.44,84.52
XS GIS Cut Line= 4
     609343.3331    4324036.3031     609332.0815    4323992.3298
     609328.1014    4323982.8218     609285.3893    4323910.8903
#Sta/Elev= 30
       0  595.08    3.03  593.77   18.16  584.57   21.18  582.44   24.21  579.73
   27.23  576.62   30.26  574.18   33.29   573.2   36.31  569.64   39.34  566.39
   42.36  565.88   45.39  566.45   47.97  566.66   58.69  567.19   70.64  567.58
   82.59  568.17   85.57  568.48   88.56  569.24   91.55  570.32   94.54   570.7
  100.51  572.59  106.49  574.18  109.48  575.22  112.46  577.49  115.45     580
  121.43  583.36  124.42  584.68   127.4  585.48  133.38  589.16  139.35  593.15
#Mann= 3 , 0 , 0
       0      .1       0   39.34      .1       0   47.97      .1       0
Bank Sta=39.34,47.97
XS Rating Curve= 0 ,0
Exp/Cntr=0.3,0.1

Type RM Length L Ch R = 1 ,1737.36 ,81.28,91.44,95.4
XS GIS Cut Line= 4
     609430.1401     4323951.853     609393.6212    4323926.3782
      609384.586    4323921.7232     609345.3969    4323869.3771
#Sta/Elev= 30
       0  584.77    5.94  581.29    8.91   579.2   11.87  576.49   20.78  570.57
   23.75  569.73   26.72   568.6   29.68  566.58   32.65  564.84   35.62   563.5
   38.59  562.76   46.07  562.25   54.69  561.53   57.66  561.55   60.63  562.13
   66.58  563.39    75.5  564.15   78.47  564.68   81.44  565.81   84.41  567.35
   87.39  569.73   90.36  572.37   93.33  574.63    96.3  576.45   99.27  577.66
  102.25  578.35  111.16  581.59  114.14  583.19  117.11  585.28  120.08  586.99
#Mann= 3 , 0 , 0
       0      .1       0   46.07      .1       0   60.63      .1       0
Bank Sta=46.07,60.63
XS Rating Curve= 0 ,0
Exp/Cntr=0.3,0.1

Type RM Length L Ch R = 1 ,1645.92 ,84.07,91.44,87.26
XS GIS Cut Line= 5
     609473.9846    4323928.9085     609460.2777    4323888.8692
     609458.7696    4323874.4819     609459.0454    4323866.0035
      609452.602    4323823.4524
#Sta/Elev= 22
       0  584.49    3.02  583.12    9.07  579.01   12.09  576.74   15.11  573.64
   18.14  570.28   21.16   567.6   24.18  565.46   27.21  563.96   33.25  563.58
   62.44  563.14   65.27  562.94   68.34  562.31   71.42  561.33   74.49  562.95
   77.57  566.13   80.64   568.8   86.79  572.68   89.86  572.78   96.01  576.61
   99.08  578.65  108.31  585.06
#Mann= 3 , 0 , 0
       0      .1       0   68.34      .1       0   74.49      .1       0
Bank Sta=68.34,74.49
XS Rating Curve= 0 ,0
Exp/Cntr=0.3,0.1

Type RM Length L Ch R = 1 ,1554.48 ,91.47,91.44,71.42
XS GIS Cut Line= 4
     609549.4513    4323901.2694     609533.0556    4323846.6472
     609533.7606    4323833.2532      609530.341    4323797.1457
#Sta/Elev= 25
       0  574.04       3  572.56       6  570.79       9  569.72   12.01  568.99
   15.01  567.06   18.01  565.26   21.01  563.63   24.01  562.49   27.01  562.07
   36.02  561.42   39.02  561.26   42.02  561.24   57.03  560.67   65.08  560.28
   70.44  560.15   73.46  559.98   76.49  560.17   79.51  561.73   82.53  564.17
   85.55  566.37   97.64  573.86  100.67  574.84  103.69  575.93  106.71  578.01
#Mann= 3 , 0 , 0
       0      .1       0   65.08      .1       0   76.49      .1       0
Bank Sta=65.08,76.49
XS Rating Curve= 0 ,0
Exp/Cntr=0.3,0.1

Type RM Length L Ch R = 1 ,1463.04 ,70.1,91.44,94.78
XS GIS Cut Line= 5
      609645.435    4323855.8833     609613.7505    4323825.5543
     609599.7552    4323817.6889     609590.0393    4323814.2882
     609547.8035    4323788.4145
#Sta/Elev= 28
       0  576.24    5.85  572.59    8.77  571.33    11.7  570.59   14.62  568.46
   17.54  565.91   23.39   562.3   26.32  560.83   29.24  560.16   40.94   559.1
   43.86  558.88   49.21  558.69   54.56  558.32   59.91  557.92   65.06  557.37
   67.64  557.28   76.04  557.22   78.95  557.36   81.86  557.87   84.78  559.36
    90.6  561.51   93.52  562.71   96.43  563.61   99.34  564.36  102.26  565.68
  108.09  569.88  113.91  573.33  119.74  576.55
#Mann= 3 , 0 , 0
       0      .1       0   65.06      .1       0   78.95      .1       0
Bank Sta=65.06,78.95
XS Rating Curve= 0 ,0
Exp/Cntr=0.3,0.1

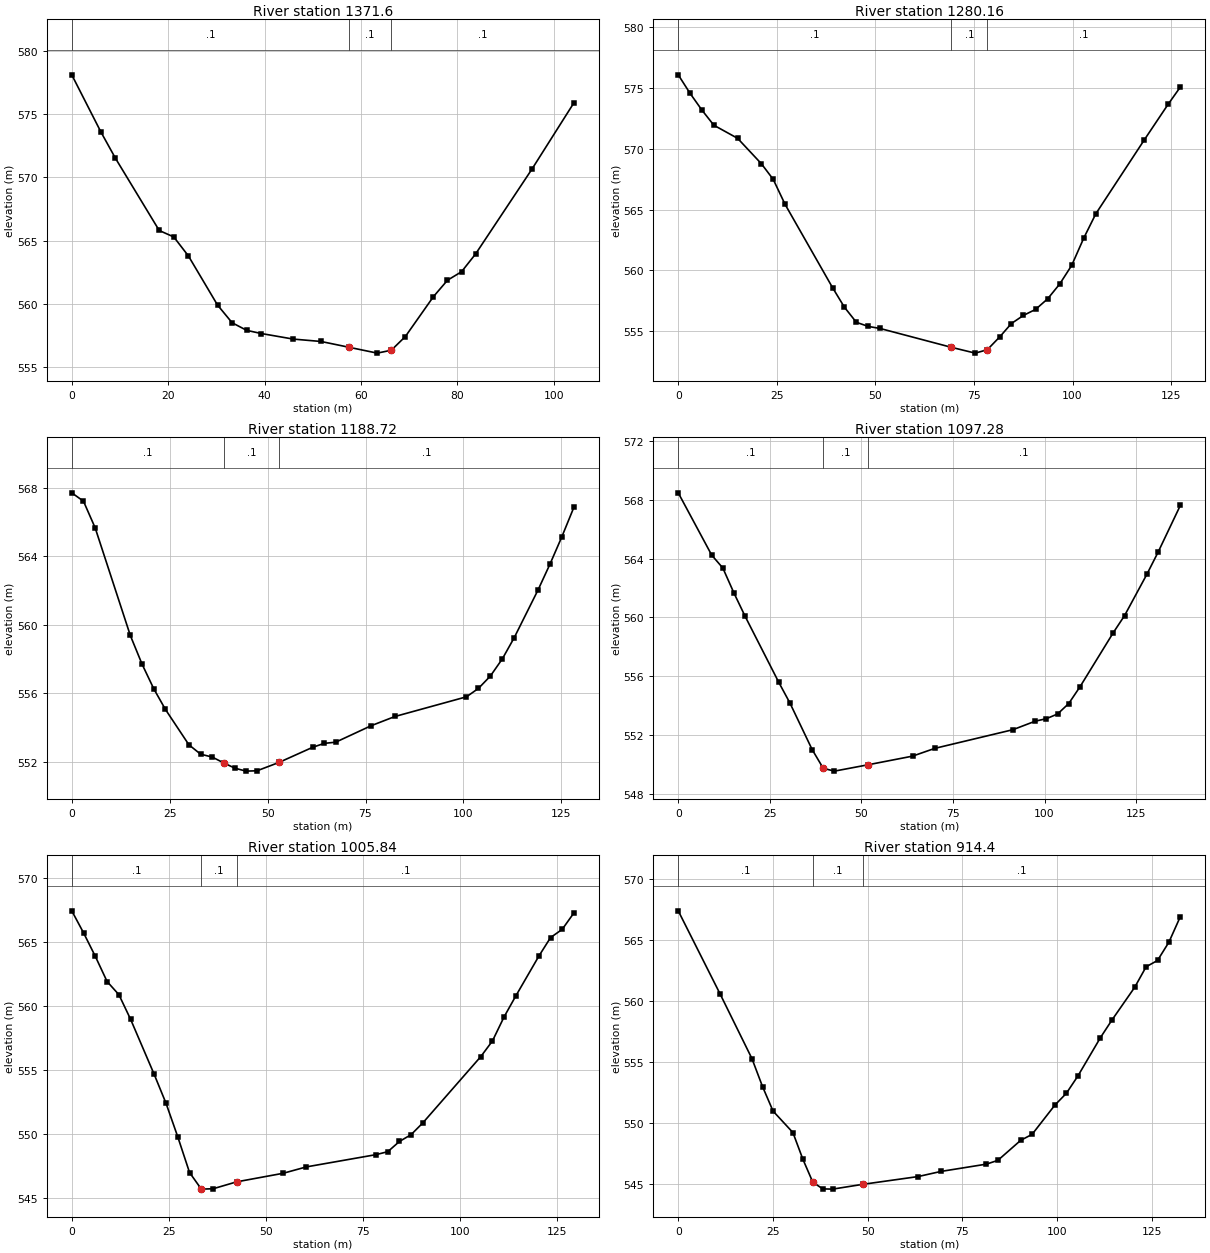
Type RM Length L Ch R = 1 ,1371.6  ,96.81,91.44,86.85
XS GIS Cut Line= 5
     609676.3913    4323835.2458     609666.9949    4323797.0842
     609666.5683    4323793.3601     609665.1429    4323787.7882
     609647.8162    4323735.2331
#Sta/Elev= 22
       0   578.1    6.05  573.58    9.07   571.5   18.14   565.8   21.16  565.29
   24.19  563.79   30.23  559.91   33.26  558.51   36.28  557.91    39.3  557.66
   45.93  557.22   51.71  557.03   57.54  556.57   63.36  556.11   66.28  556.34
   69.19  557.42   75.01  560.57   77.93  561.87   80.84  562.54   83.75  563.94
    95.4  570.62  104.14  575.88
#Mann= 3 , 0 , 0
       0      .1       0   57.54      .1       0   66.28      .1       0
Bank Sta=57.54,66.28
XS Rating Curve= 0 ,0
Exp/Cntr=0.3,0.1

Type RM Length L Ch R = 1 ,1280.16 ,81.44,91.44,88.13
XS GIS Cut Line= 3
     609784.3415    4323782.0644     609733.5416    4323730.6689
     609692.6151    4323693.8351
#Sta/Elev= 28
       0   576.1    3.01  574.57    6.02  573.19    9.03  571.95   15.06  570.87
   21.08  568.78   24.09  567.49    27.1  565.43   39.14  558.57   42.15  556.96
   45.17  555.72   48.18  555.38   51.19  555.21   69.25  553.66   75.32  553.18
   78.38  553.46   81.54  554.52    84.5  555.62   87.56  556.29   90.62  556.78
   93.68  557.65   96.74  558.87   99.79  560.41  102.85  562.66  105.91  564.66
  118.15  570.72  124.27  573.69  127.33  575.09
#Mann= 3 , 0 , 0
       0      .1       0   69.25      .1       0   78.38      .1       0
Bank Sta=69.25,78.38
XS Rating Curve= 0 ,0
Exp/Cntr=0.3,0.1

Type RM Length L Ch R = 1 ,1188.72 ,92.94,91.44,83.07
XS GIS Cut Line= 5
     609826.2119    4323740.4807     609810.3394    4323704.9996
      609802.588     4323686.913     609799.6308    4323675.5031
     609761.7567    4323631.7701
#Sta/Elev= 29
       0  567.69    2.99   567.2    5.98  565.64   14.95  559.36   17.94  557.69
   20.93  556.25   23.92  555.04    29.9  552.98   32.89  552.43   35.88  552.26
   38.87  551.91   41.68  551.61   44.49  551.44    47.3  551.46   52.93  551.95
   61.49  552.83   64.44  553.06   67.39  553.13   76.42  554.09   82.51  554.63
  100.78  555.78  103.83  556.27  106.87  556.99  109.92  557.99  112.96  559.23
  119.05  562.02   122.1  563.53  125.14  565.13  128.19  566.84
#Mann= 3 , 0 , 0
       0      .1       0   38.87      .1       0   52.93      .1       0
Bank Sta=38.87,52.93
XS Rating Curve= 0 ,0
Exp/Cntr=0.3,0.1

Type RM Length L Ch R = 1 ,1097.28 ,91.85,91.44,89.88
XS GIS Cut Line= 2
     609907.9633    4323676.2895     609814.1823    4323576.3388
#Sta/Elev= 24
       0  568.48    9.14  564.24   12.18  563.36   15.23  561.65   18.27  560.07
   27.41   555.6   30.46  554.19   36.55  551.01   39.59  549.73   42.64  549.54
   51.78  549.97   63.96  550.56   70.05  551.09   91.37  552.36   97.46  552.94
  100.51  553.11  103.56  553.43   106.6  554.14  109.65  555.27  118.78  558.97
  121.83  560.12  127.92  562.93  130.97  564.43  137.06  567.62
#Mann= 3 , 0 , 0
       0      .1       0   39.59      .1       0   51.78      .1       0
Bank Sta=39.59,51.78
XS Rating Curve= 0 ,0
Exp/Cntr=0.3,0.1

Type RM Length L Ch R = 1 ,1005.84 ,87.65,91.44,94.66
XS GIS Cut Line= 3
     609971.9865    4323606.6508     609940.0888    4323578.6589
     609878.6651    4323517.3732
#Sta/Elev= 28
       0  567.46    3.03  565.74    6.06   563.9    9.09  561.93   12.13   560.9
   15.16  558.96   21.22  554.66   24.25  552.41   27.28  549.78   30.31  546.99
   33.34  545.69   36.38  545.72   42.44  546.26   54.41  546.93   60.39  547.43
   78.34  548.39   81.33  548.62   84.33  549.42   87.32  549.95   90.31  550.86
  105.27  556.06  108.26  557.28  111.25  559.16  114.25  560.79  120.23  563.93
  123.22  565.37  126.21  566.01  129.21  567.29
#Mann= 3 , 0 , 0
       0      .1       0   33.34      .1       0   42.44      .1       0
Bank Sta=33.34,42.44
XS Rating Curve= 0 ,0
Exp/Cntr=0.3,0.1

Type RM Length L Ch R = 1 ,914.4   ,97.54,91.44,89.97
XS GIS Cut Line= 5
     610028.1749    4323558.2581     610012.9462    4323538.3988
      610010.157    4323525.5939     610004.9785    4323513.5106
     609963.5309    4323443.6176
#Sta/Elev= 27
       0  567.36   11.12   560.5   19.46  555.24   22.25  552.95   25.03  550.94
   30.27  549.18   32.89     547   35.51  545.12   38.13  544.56   40.76  544.54
   48.65  544.93   63.32  545.57   69.33  545.99   81.37  546.59   84.38   546.9
    90.4  548.54   93.41  549.03   99.43  551.43  102.44  552.39  105.45  553.79
  111.47  556.97  114.48   558.4   120.5  561.09  123.51  562.77  126.52  563.29
  129.53  564.79  132.54  566.88
#Mann= 3 , 0 , 0
       0      .1       0   35.51      .1       0   48.65      .1       0
Bank Sta=35.51,48.65
XS Rating Curve= 0 ,0
Exp/Cntr=0.3,0.1

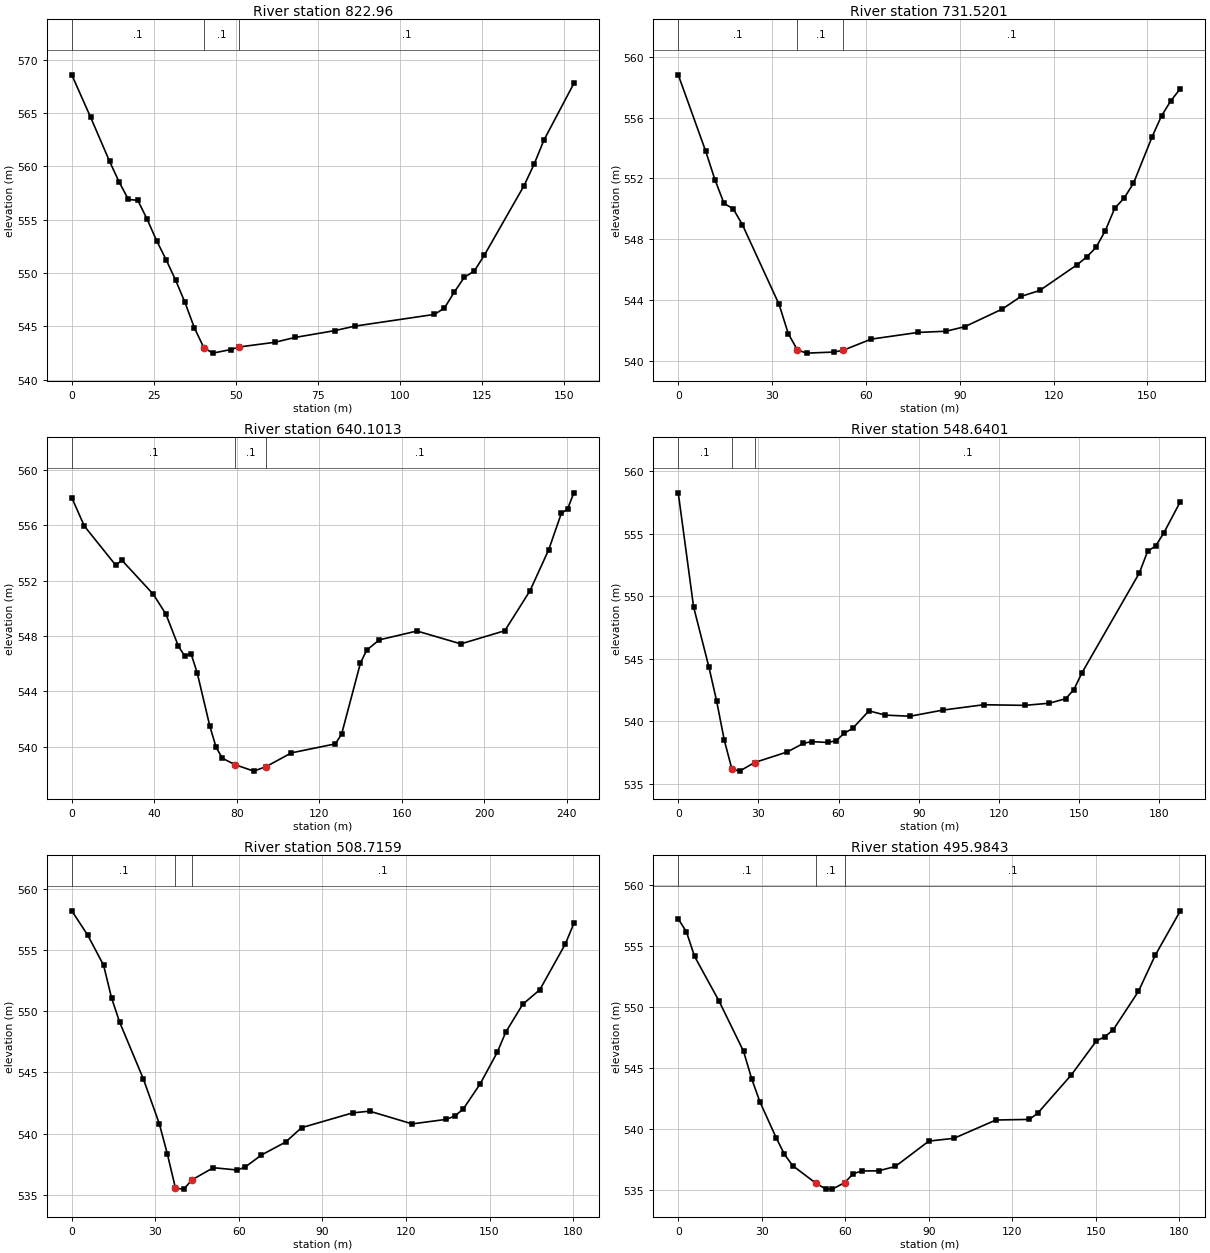
Type RM Length L Ch R = 1 ,822.96  ,90.73,91.44,95.09
XS GIS Cut Line= 4
     610118.4845    4323506.0991     610089.2553    4323478.4855
     610077.3704    4323460.3452     610023.3295    4323387.1695
#Sta/Elev= 30
       0  568.57    5.74  564.59   11.49  560.47   14.36  558.56   17.23  556.89
   20.11   556.8   22.98  555.01   25.85  553.01   28.72  551.24   31.59  549.34
   34.47  547.23   37.34  544.84   40.21  542.99   42.92  542.48   48.34  542.81
   51.05  543.06    61.9   543.5   67.96  543.95   80.09  544.59   86.16  545.01
  110.41  546.11  113.45   546.7  116.48  548.21  119.51  549.59  122.54  550.17
  125.57  551.64   137.7  558.18  140.74  560.18  143.77  562.46  152.86  567.76
#Mann= 3 , 0 , 0
       0      .1       0   40.21      .1       0   51.05      .1       0
Bank Sta=40.21,51.05
XS Rating Curve= 0 ,0
Exp/Cntr=0.3,0.1

Type RM Length L Ch R = 1 ,731.5201,90.89,91.42,94.78
XS GIS Cut Line= 3
     610189.7752    4323469.9951      610161.286    4323422.1513
     610121.6595    4323325.1237
#Sta/Elev= 30
       0  558.81    8.79  553.78   11.72  551.92   14.65  550.35   17.58     550
   20.52  548.95   32.24  543.71   35.17  541.79    38.1  540.72   41.03  540.51
   49.82  540.58   52.75   540.7   61.67  541.43   76.65  541.87   85.63  541.95
   91.62  542.25   103.6  543.41  109.58  544.24  115.57  544.63  127.55  546.33
  130.55  546.83  133.54  547.46  136.54  548.57  139.53  550.04  142.52   550.7
  145.52  551.68  151.51  554.75   154.5  556.12   157.5  557.11  160.49   557.9
#Mann= 3 , 0 , 0
       0      .1       0    38.1      .1       0   52.75      .1       0
Bank Sta=38.1,52.75
XS Rating Curve= 0 ,0
Exp/Cntr=0.3,0.1

Type RM Length L Ch R = 1 ,640.1013,96.48,91.46,76.97
XS GIS Cut Line= 2
     610286.8224    4323495.7575     610203.4159    4323267.1798
#Sta/Elev= 30
       0  557.99    6.08  555.94   21.29  553.11   24.33  553.46   39.54     551
   45.62  549.57   51.71  547.24   54.75  546.54   57.79  546.72   60.83   545.3
   66.91  541.47   69.95  539.94      73  539.15   79.08  538.69    88.2  538.22
   94.24  538.55  106.45  539.54  127.74  540.19  130.78   540.9  139.91  546.04
  142.95  546.97  149.03  547.71  167.28  548.35  188.57  547.42  209.86  548.37
  222.03  551.25  231.15  554.23  237.24  556.85  240.28  557.17  243.32  558.34
#Mann= 3 , 0 , 0
       0      .1       0   79.08      .1       0   94.24      .1       0
Bank Sta=79.08,94.24
XS Rating Curve= 0 ,0
Exp/Cntr=0.3,0.1

Type RM Length L Ch R = 1 ,548.6401,40.05,39.92,33.18
XS GIS Cut Line= 4
     610359.8663    4323373.2343      610328.383    4323370.9118
     610314.8884    4323363.7789     610217.7034    4323261.6236
#Sta/Elev= 30
       0  558.26    5.74  549.14   11.48  544.32   14.35  541.62   17.22  538.48
   20.09  536.15   22.96     536   28.58  536.69   40.73  537.53   46.83  538.22
    49.9  538.36   56.03  538.29   59.09  538.44   62.16  539.04   65.22  539.41
   71.35  540.82   77.48  540.48   86.68  540.39   98.94  540.88  114.27  541.31
  129.59  541.26  138.79  541.43  144.92  541.79  147.98  542.51  151.05  543.87
  172.51  551.85  175.57  553.57  178.64  554.02   181.7  555.07  187.83  557.55
#Mann= 3 , 0 , 0
       0      .1       0   20.09      .1       0   28.58      .1       0
Bank Sta=20.09,28.58
XS Rating Curve= 0 ,0
Exp/Cntr=0.3,0.1

Type RM Length L Ch R = 1 ,508.7159,14.85,12.73,11.82
XS GIS Cut Line= 6
     610376.4281    4323330.9869     610333.2692    4323331.3548
     610331.2054    4323335.4823     610328.1891    4323335.0061
     610298.6661    4323323.5362     610226.4347    4323257.6548
#Sta/Elev= 30
       0   558.2    5.71  556.22   11.43  553.75   14.28  551.09   17.14  549.13
   25.71  544.46   31.42  540.81   34.28  538.37   37.24  535.53   40.21  535.46
   43.17  536.22   50.84  537.21   59.48  537.02   62.36  537.28   68.12  538.25
   76.75   539.3   82.51  540.48  100.84  541.69  106.95  541.83  122.23  540.79
  134.45  541.16   137.5  541.43  140.56     542  146.67  544.07  152.78  546.64
  155.84  548.29  161.95  550.57  168.06  551.75  177.22  555.49  180.28  557.17
#Mann= 3 , 0 , 0
       0      .1       0   37.24      .1       0   43.17      .1       0
Bank Sta=37.24,43.17
XS Rating Curve= 0 ,0
Exp/Cntr=0.3,0.1

Type RM Length L Ch R = 1 ,495.9843,34.81,38.81,44.71
XS GIS Cut Line= 6
     610388.6697    4323321.2708     610341.9343    4323316.6572
     610338.1243    4323316.9747     610332.4093    4323323.4834
     610329.2343    4323323.6422     610239.9285     4323247.336
#Sta/Elev= 30
       0  557.22    2.94  556.16    5.87  554.14   14.68  550.47   23.48  546.35
   26.42  544.08   29.35  542.21   35.22  539.25   38.16  537.91   41.09  536.98
   49.56  535.52   53.08  535.05   55.37  535.05   59.77  535.58   62.95  536.32
   65.97  536.54   71.99  536.55   78.01  536.91   90.06  538.99    99.1  539.22
  114.16  540.72   126.2  540.77  129.22  541.29  141.26  544.42   150.3  547.22
  153.31  547.55  156.32  548.12  165.36  551.27  171.38  554.22  180.42  557.88
#Mann= 3 , 0 , 0
       0      .1       0   49.56      .1       0   59.77      .1       0
Bank Sta=49.56,59.77
XS Rating Curve= 0 ,0
Exp/Cntr=0.3,0.1

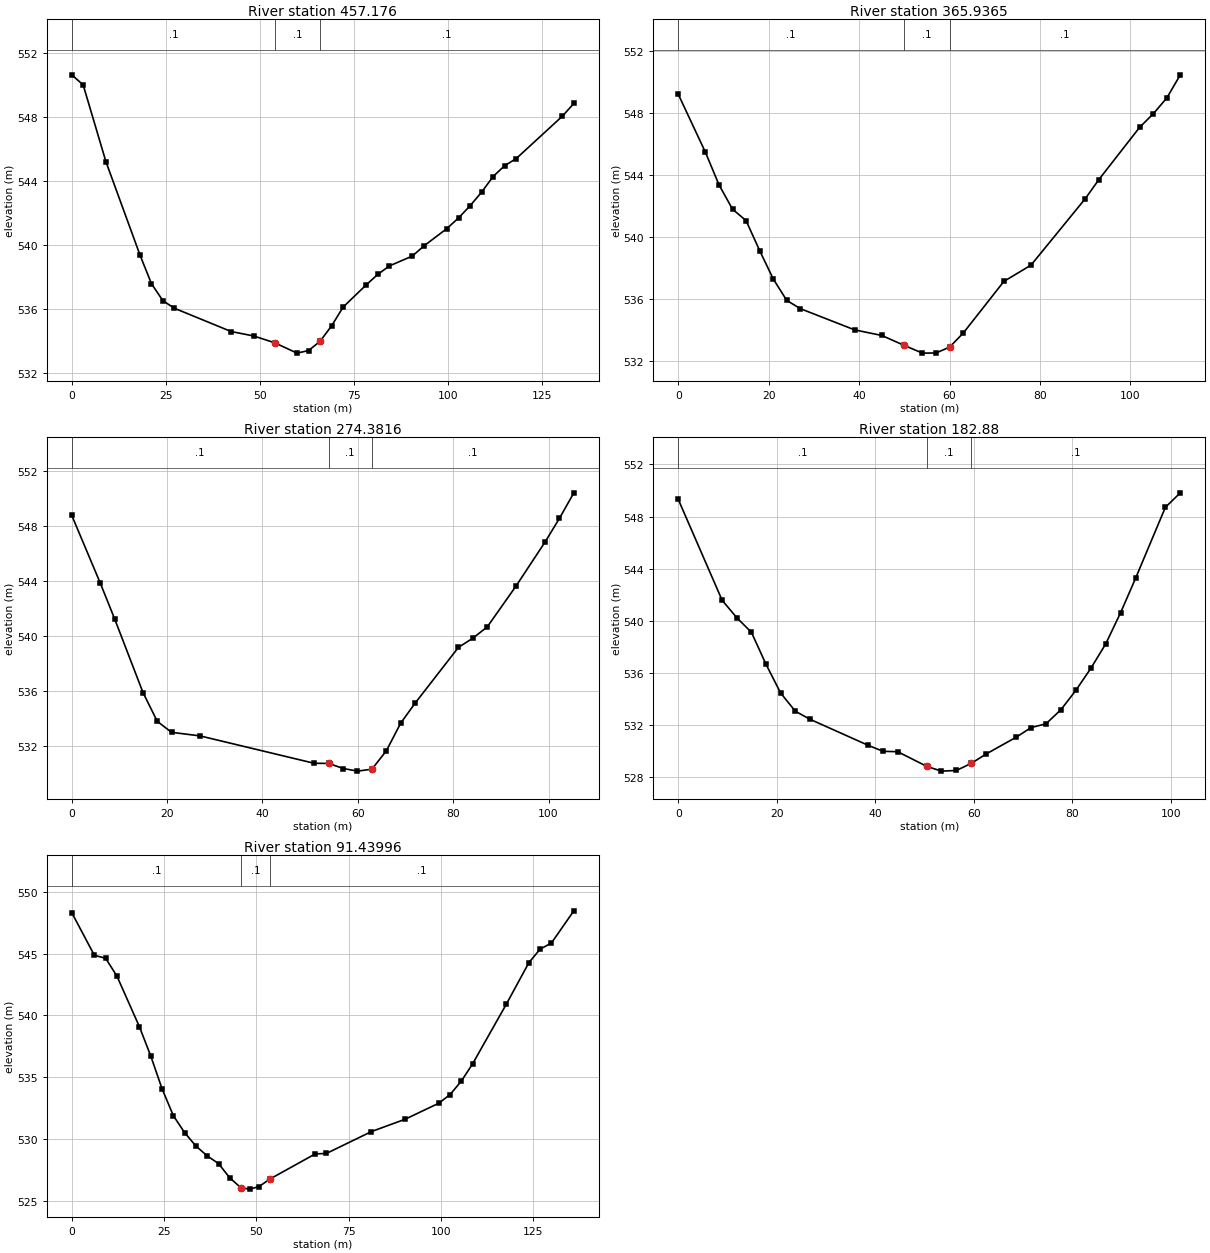
Type RM Length L Ch R = 1 ,457.176 ,78.14,91.24,94.2
XS GIS Cut Line= 4
     610389.2034    4323308.8447     610348.8544    4323282.0556
     610340.4891    4323281.3437     610268.3448    4323255.3926
#Sta/Elev= 29
       0  550.63    3.03     550    9.08   545.2   18.16  539.35   21.19  537.57
   24.22  536.51   27.24  536.04   42.38  534.58   48.43   534.3   54.03  533.87
   59.89  533.23   62.96  533.39   66.03  533.97    69.1  534.94   72.16  536.11
    78.3   537.5   81.36  538.15   84.43  538.68   90.56   539.3   93.63  539.93
   99.76  541.02  102.83  541.68   105.9  542.44  108.96  543.29  112.03  544.27
   115.1  544.95  118.16  545.39  130.43  548.04   133.5  548.84
#Mann= 3 , 0 , 0
       0      .1       0   54.03      .1       0   66.03      .1       0
Bank Sta=54.03,66.03
XS Rating Curve= 0 ,0
Exp/Cntr=0.3,0.1

Type RM Length L Ch R = 1 ,365.9365,90.17,91.55,91.9
XS GIS Cut Line= 2
     610434.2389    4323286.3489      610395.345    4323182.3675
#Sta/Elev= 24
       0  549.23       6  545.49       9  543.39      12  541.81      15  541.07
      18  539.14      21  537.31      24  535.92      27  535.39   39.01  534.02
   45.01  533.66   49.95  533.02   54.01  532.52   57.01  532.53   60.01  532.91
   63.01  533.81   72.01  537.15   78.01   538.2   90.01  542.49   93.01  543.72
  102.02  547.09  105.02  547.96  108.02  548.98  111.02  550.48
#Mann= 3 , 0 , 0
       0      .1       0   49.95      .1       0   60.01      .1       0
Bank Sta=49.95,60.01
XS Rating Curve= 0 ,0
Exp/Cntr=0.3,0.1

Type RM Length L Ch R = 1 ,274.3816,89.08,91.5,92.25
XS GIS Cut Line= 3
      610517.465    4323256.4863     610502.5228    4323211.0645
      610488.214    4323155.3799
#Sta/Elev= 22
       0  548.76    5.98  543.84    8.97  541.26   14.94  535.89   17.93   533.8
   20.92     533    26.9  532.74   50.84  530.75   53.87  530.74   56.96  530.37
   59.92  530.18   62.95  530.32   65.97  531.65      69  533.67   72.02  535.12
    81.1  539.17   84.13  539.84   87.15  540.66   93.21  543.64   99.26  546.82
  102.28  548.54  105.31   550.4
#Mann= 3 , 0 , 0
       0      .1       0   53.87      .1       0   62.95      .1       0
Bank Sta=53.87,62.95
XS Rating Curve= 0 ,0
Exp/Cntr=0.3,0.1

Type RM Length L Ch R = 1 ,182.88  ,92.37,91.44,91.16
XS GIS Cut Line= 4
     610594.6463    4323237.2028     610590.5708     4323192.817
      610590.489    4323183.9277     610584.6108    4323135.7838
#Sta/Elev= 27
       0  549.32    8.91  541.58   11.89  540.24   14.86  539.12   17.83  536.66
    20.8  534.46   23.77  533.07   26.74  532.45   38.63  530.44    41.6  529.99
   44.57  529.96    50.5  528.83   53.46  528.47   56.49  528.52   59.52  529.07
   62.56  529.79   68.62  531.07   71.65  531.81   74.68   532.1   77.71  533.18
   80.74  534.66   83.78  536.35   86.81  538.23   89.84  540.63   92.87  543.26
   98.93  548.71  101.96  549.82
#Mann= 3 , 0 , 0
       0      .1       0    50.5      .1       0   59.52      .1       0
Bank Sta=50.5,59.52
XS Rating Curve= 0 ,0
Exp/Cntr=0.3,0.1

Type RM Length L Ch R = 1 ,91.43996,69.4,91.44,53.42
XS GIS Cut Line= 4
     610688.6718    4323221.1884     610681.0396    4323175.9543
     610680.9544    4323171.1024     610662.0456     4323087.911
#Sta/Elev= 30
       0  548.32    6.12  544.87    9.17  544.63   12.23  543.19   18.35  539.07
   21.41  536.71   24.47  534.06   27.52  531.89   30.58  530.51   33.64  529.43
    36.7  528.63   39.76  528.01   42.82  526.85   45.87  526.04    48.3  525.94
   50.73  526.15   53.77  526.77   65.96  528.79   69.01  528.83    81.2   530.6
   90.34   531.6   99.48   532.9  102.52   533.6  105.57  534.69  108.62  536.09
  117.76  540.92  123.85  544.27   126.9  545.37  129.95  545.86  136.04  548.47
#Mann= 3 , 0 , 0
       0      .1       0   45.87      .1       0   53.77      .1       0
Bank Sta=45.87,53.77
XS Rating Curve= 0 ,0
Exp/Cntr=0.3,0.1
LCMann Table=0

Chan Stop Cuts=-1
Use User Specified Reach Order=0
Composite Channel Slope=5